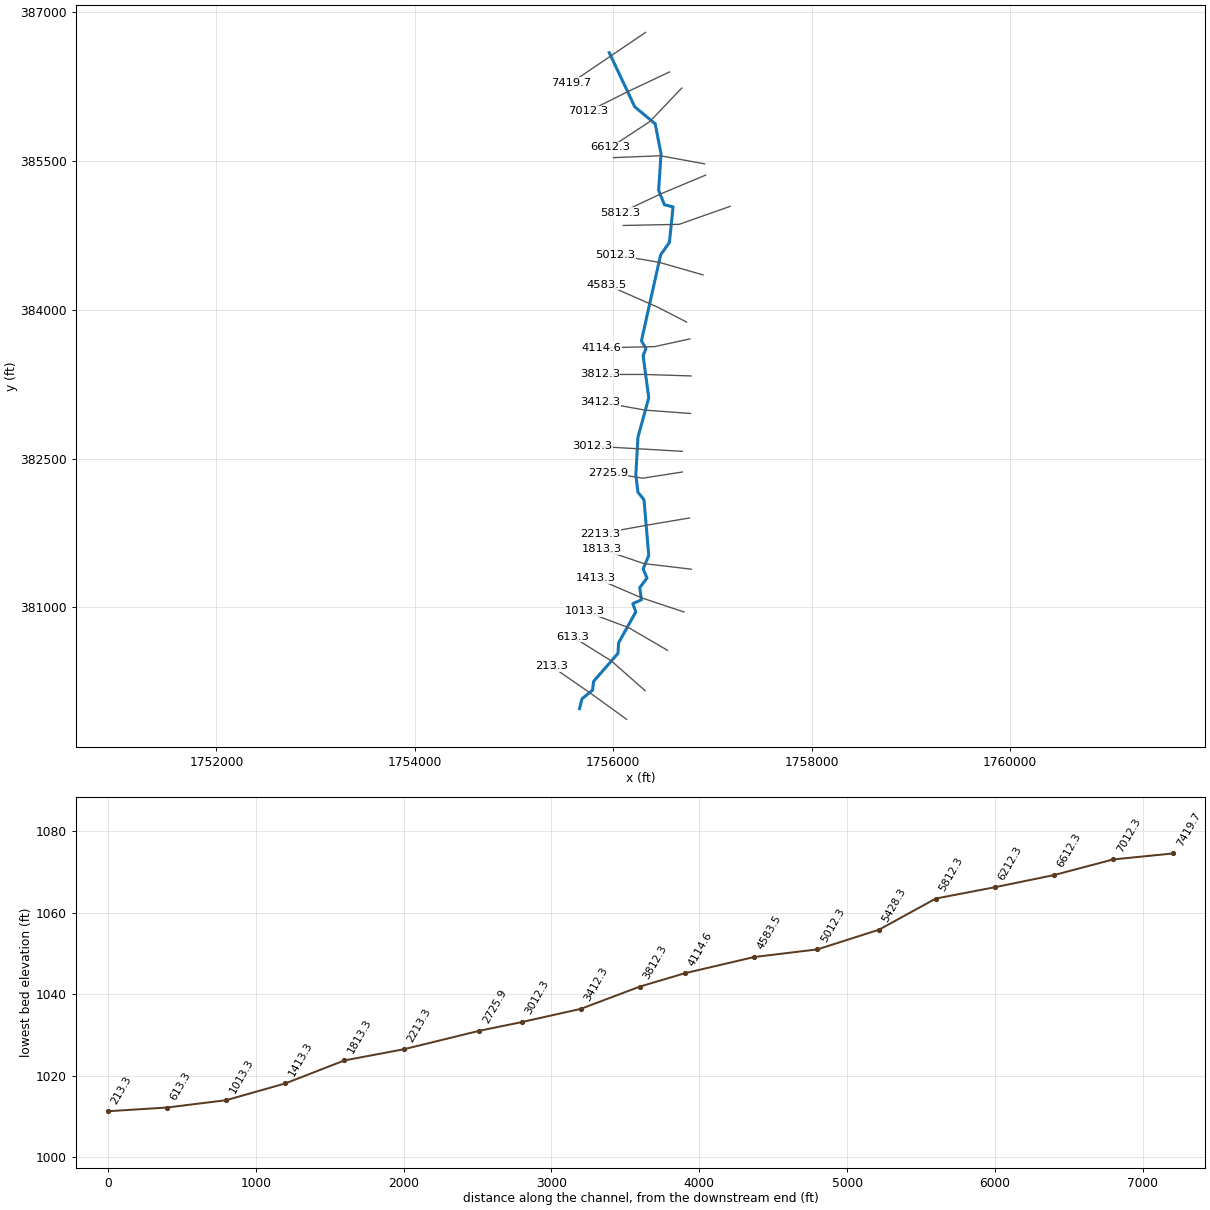
--- NP10.prj (project) ---

Proj Title=NP10
Current Plan=p01
Default Exp/Contr=0,0
English Units
Geom File=g01
Flow File=f01
Plan File=p01
BEGIN DESCRIPTION:
END DESCRIPTION:
DSS Export Rating Curves= 0
DSS Export Rating Curve Sorted= 0
DSS Export Volume Flow Curves= 0
DXF OffsetX= 0
DXF OffsetY= 0
DXF ScaleX= 0
DXF ScaleY= 0

--- NP10.p01 (plan) ---

Plan Title=Floodplain
Program Version=4.00
Geom File=g01
Flow File=f01
K Sum by GR=0
Std Step Tol=0.01
Critical Tol=0.01
Num of Std Step Trials=20
Max Error Tol=0.3
Flow Tol Ratio=0.001
Split Flow NTrial=30
Split Flow Tol=0.02
Split Flow Ratio=0.02
Log Output Level=0
Friction Slope Method=1
Unsteady Friction Slope Method=2
Unsteady Bridges Friction Slope Method=1
Global Log Level=0
CheckData=False
Run HTab=0
Run UNet=0
Run PostProcess=0
UNET Theta=0
UNET Theta Warmup=0
UNET ZTol=0
UNET ZSATol=0
UNET MxIter=0
UNET MaxInSteps=0
UNET DtIC=0
UNET DtMin=0
UNET MaxCRTS=0
UNET WFStab=0
UNET SFStab=0
UNET WFX=0
UNET SFX=0
UNET DSS MLevel=0
UNET DZMax Abort=0
UNET Convert EG Bridges=0
UNET Use Existing IB Tables=0
UNET Froude Limit=0
UNET Froude Power=0
Write IC File=0
Echo Input=False
Echo Output=False
Write Detailed=0

--- NP10.f01 (steady flow) ---

Flow Title=NFF Regression Equation
Program Version=4.00
Number of Profiles= 1
Profile Names=P100yr
River Rch & RM=NP10,Main            ,7419.7
 734.788
River Rch & RM=NP10,Main            ,6612.3
 768.173
River Rch & RM=NP10,Main            ,5012.3
843.7612
River Rch & RM=NP10,Main            ,4114.6
 918.619
River Rch & RM=NP10,Main            ,2725.9
954.5188
River Rch & RM=NP10,Main            ,213.3
1057.102
Boundary for River Rch & Prof#=NP10,Main            , 1
Up Type= 0
Dn Type= 3
Dn Slope=0.007495
DSS Import GetInterval= 0
DSS Import GetPeak= 0
DSS Import FillOption= 0

--- NP10.g01 (geometry) ---

Geom Title=USGS 3m DEM
Program Version=4.00

River Reach=NP10            ,Main
Reach XY= 30
     1755960.119      386592.476     1756216.854      386046.839
     1756423.017      385875.398     1756481.611      385573.749
      1756457.74      385204.825     1756516.333      385059.426
     1756603.139      385037.724     1756566.247      384679.652
     1756477.271      384553.783     1756284.128      383687.898
     1756329.701      383609.773      1756301.49      383538.158
     1756357.913      383112.811     1756249.406      382717.846
     1756227.705      382340.242     1756248.772      382161.909
      1756310.18      382084.973     1756357.913      381524.269
      1756301.49      381387.551     1756340.552      381296.405
     1756266.767      381198.749     1756284.128      381077.221
     1756197.323      381038.158     1756227.705      380955.693
     1756054.094      380643.193     1756047.583      380536.856
     1755802.358      380254.738     1755791.507      380165.763
      1755685.17      380078.957     1755660.091      379979.668

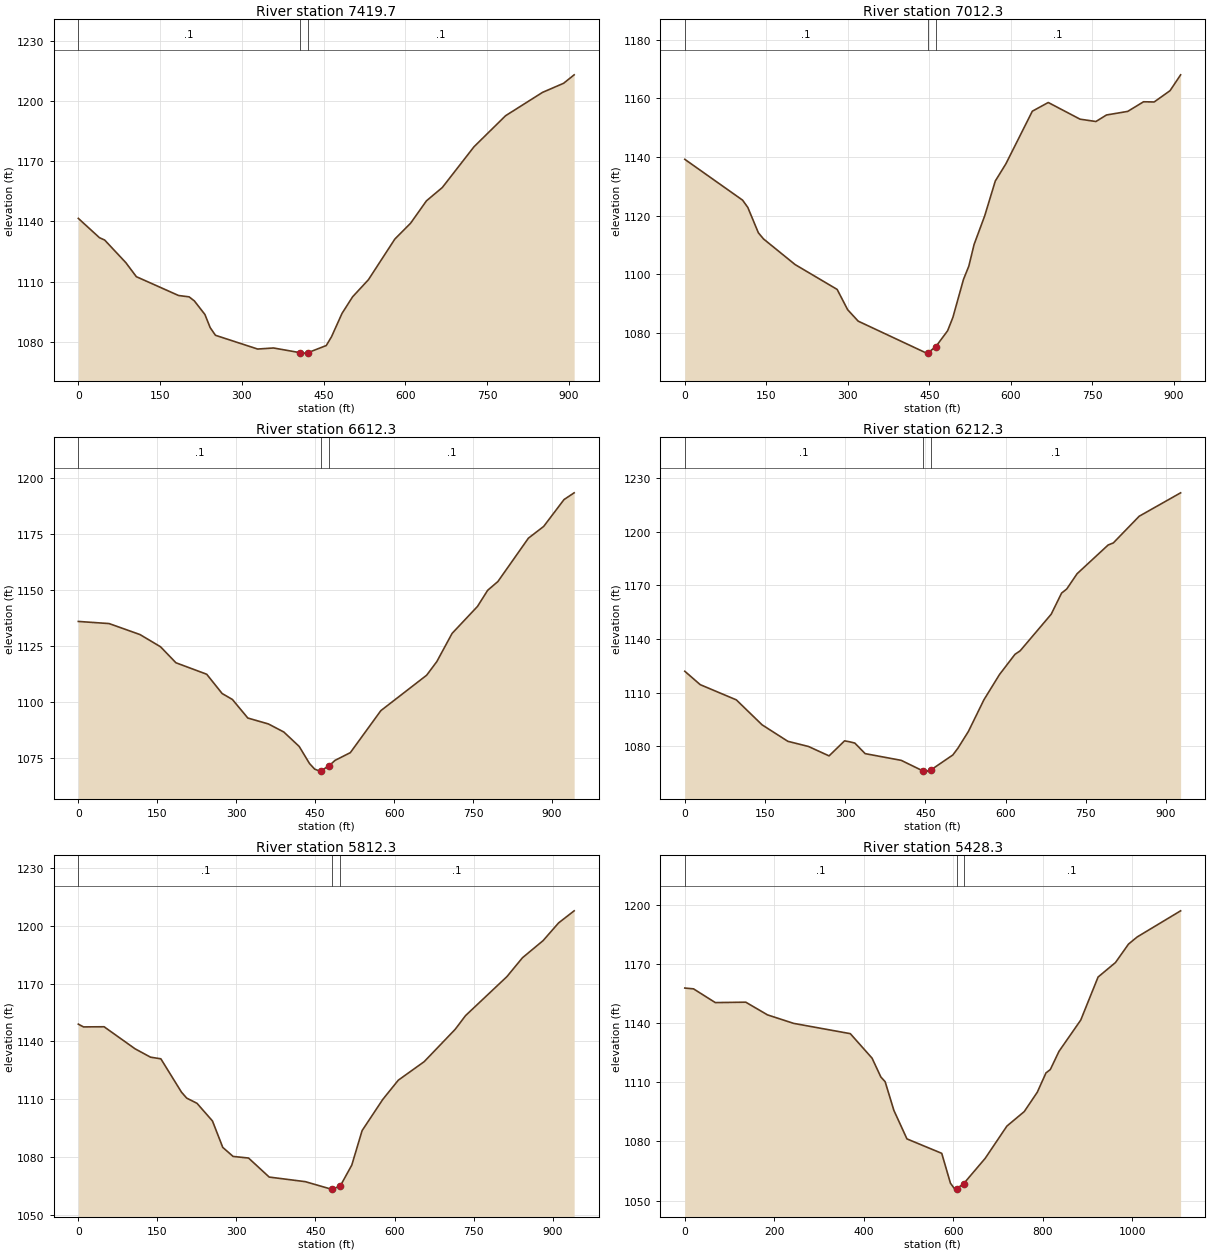
Type RM Length L Ch R = 1 ,7419.7  ,411.04,407.356,404.192
XS GIS Cut Line= 3
     1756325.728      386797.218     1755949.025      386542.032
     1755572.322      386286.846
#Sta/Elev= 30
       0 1141.54    38.7 1131.96    48.4 1130.76    87.1 1119.55   106.5 1112.54
   183.9 1103.19   203.3 1102.51     213 1100.48   232.3 1093.75     242  1087.2
   251.7 1083.39   329.1 1076.55   358.2 1077.08   406.9 1074.74   416.3 1074.52
   421.9  1074.8     455 1078.29   464.7 1082.68     484  1094.3   503.4 1102.54
   532.4 1111.03   580.9 1131.25   609.9 1139.17   638.9 1150.27     668 1156.89
   726.1 1177.14   784.1  1192.6   851.9 1204.21   890.6 1208.74     910 1212.95
#Mann= 3 , 0 , 0
       0      .1       0   406.9    .045       0   421.9      .1       0
Bank Sta=406.9,421.9
XS Rating Curve= 0 ,0
Exp/Cntr=0.3,0.1

Type RM Length L Ch R = 1 ,7012.3  ,390.422,400,401.82
XS GIS Cut Line= 3
     1756567.232      386398.391     1756156.163      386204.616
     1755746.433      385999.774
#Sta/Elev= 30
       0 1139.22   106.4 1125.27     116 1122.78   135.4 1114.13     145 1112.01
   203.1 1103.27   280.4 1094.79   299.7 1087.87   319.1 1083.96   444.8 1073.04
     447 1073.08     462 1075.26   483.7 1080.69   493.4 1085.25   512.9 1098.22
   522.7 1102.74   532.4 1110.14   551.9  1119.9   571.4  1131.8   590.9 1137.67
   639.6 1155.65   668.9 1158.62   727.4 1152.93   756.6 1152.13   776.1 1154.36
   815.1 1155.58   844.3 1158.87   863.8  1158.8     893 1162.65   912.5 1168.07
#Mann= 3 , 0 , 0
       0      .1       0     447    .045       0     462      .1       0
Bank Sta=447,462
XS Rating Curve= 0 ,0
Exp/Cntr=0.3,0.1

Type RM Length L Ch R = 1 ,6612.3  ,424.489,400,386.199
XS GIS Cut Line= 3
     1756690.963      386235.948     1756367.497       385897.21
     1755971.704      385637.174
#Sta/Elev= 30
       0 1136.07    58.5 1135.11   117.1 1130.21   156.1 1124.76   185.4 1117.61
   243.9 1112.48   273.2 1103.87   292.7 1101.21     322 1092.92     361 1090.29
   390.3 1086.69   419.6 1080.23   439.1 1072.63   448.9 1070.12   458.6 1069.21
   460.9 1069.39   475.9 1071.51   487.7 1074.02   516.7 1077.46   574.7 1096.23
   661.7 1112.05     681 1118.13     710 1130.72   758.3 1142.78   777.6 1149.98
     797 1153.88     855 1173.26     884  1178.5   922.6 1190.49   941.9 1193.51
#Mann= 3 , 0 , 0
       0      .1       0   460.9    .045       0   475.9      .1       0
Bank Sta=460.9,475.9
XS Rating Curve= 0 ,0
Exp/Cntr=0.3,0.1

Type RM Length L Ch R = 1 ,6212.3  ,385.571,400,410.131
XS GIS Cut Line= 3
     1756921.342      385471.834     1756475.675      385553.567
     1756001.609      385534.379
#Sta/Elev= 30
       0 1121.99    28.9 1114.51    96.4 1106.02   144.6 1092.08   192.8 1082.88
   231.4 1079.99   269.9 1074.74   298.9 1083.14   308.5  1082.6   318.1 1081.89
   337.4    1076   404.9 1072.25   445.6 1066.33   453.1 1066.23   460.6 1066.93
   501.5 1075.26   511.2 1079.14   530.6  1088.4   559.6 1106.06   588.7 1120.15
   617.7 1131.45   627.4 1133.41   685.5 1153.86   704.9 1165.65   714.5 1167.92
   733.9 1176.45     792  1192.5   801.7 1193.66   850.1 1208.56   927.6 1221.63
#Mann= 3 , 0 , 0
       0      .1       0   445.6    .045       0   460.6      .1       0
Bank Sta=445.6,460.6
XS Rating Curve= 0 ,0
Exp/Cntr=0.3,0.1

Type RM Length L Ch R = 1 ,5812.3  ,392.334,384.013,370.502
XS GIS Cut Line= 3
     1756930.856      385358.147     1756479.336       385169.19
     1756070.948      384976.849
#Sta/Elev= 30
       0 1148.94     9.8 1147.52    48.9 1147.59   107.7 1136.16     137 1131.83
   156.6 1130.98   195.8 1113.68   205.6 1110.63   225.2 1107.92   254.5 1098.79
   274.1 1085.07   293.7 1080.39     323 1079.56   362.2  1069.7   430.7 1067.32
   479.7 1063.45     482 1063.49     497 1065.04   518.9  1075.9   538.5 1093.78
   577.8 1109.96   607.2 1119.91   656.3  1129.5   715.2 1146.28   734.8 1153.37
   813.3 1173.57   842.7 1183.32     882 1192.24   911.4 1201.42   940.9 1207.67
#Mann= 3 , 0 , 0
       0      .1       0     482    .045       0     497      .1       0
Bank Sta=482,497
XS Rating Curve= 0 ,0
Exp/Cntr=0.3,0.1

Type RM Length L Ch R = 1 ,5428.3  ,423.248,415.987,411.175
XS GIS Cut Line= 3
     1757178.651       385043.39     1756664.289      384862.321
     1756101.335      384850.463
#Sta/Elev= 30
       0 1157.73    19.5 1157.32    68.2 1150.36   136.3 1150.56     185 1144.12
   243.4 1139.82     370 1134.61   418.7 1122.17   438.2 1112.68   447.9 1110.24
   467.4 1095.72   496.6 1081.27   574.4 1073.95   593.8 1058.84   603.6 1055.81
   608.1 1056.09   623.1  1058.5   671.5 1071.41     720 1087.75   758.9 1095.13
     788 1104.94   807.4 1114.71   817.1 1116.42   836.5 1125.64   885.1 1141.49
   923.9 1163.32   962.8 1170.67   991.9 1180.01  1011.3 1183.63  1108.4 1196.87
#Mann= 3 , 0 , 0
       0      .1       0   608.1    .045       0   623.1      .1       0
Bank Sta=608.1,623.1
XS Rating Curve= 0 ,0
Exp/Cntr=0.3,0.1

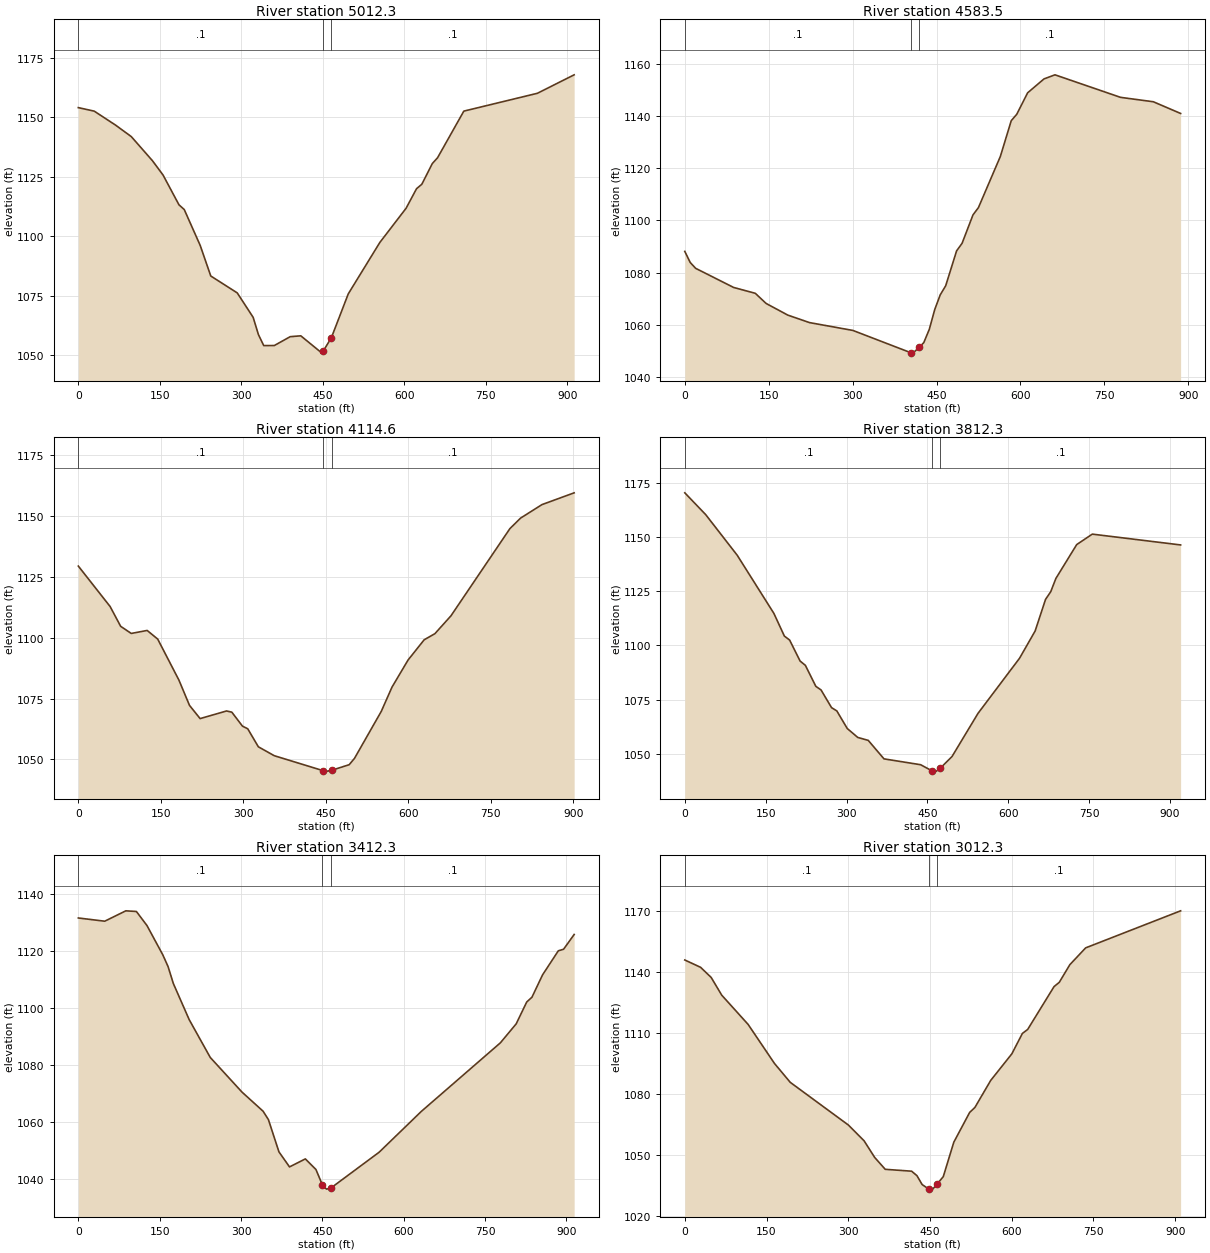
Type RM Length L Ch R = 1 ,5012.3  ,431.953,428.875,423.349
XS GIS Cut Line= 3
     1756904.907       384352.56      1756464.35      384478.717
     1756016.512      384555.804
#Sta/Elev= 30
       0 1153.99    29.3 1152.51    68.3 1146.69    97.5 1141.83   136.5  1131.7
     156 1125.69   185.3  1113.2     195 1111.22   224.3  1096.2   243.8 1083.35
   292.5 1076.26   321.8 1066.01   331.5 1058.77   341.3 1054.15   360.8 1054.18
     390 1057.89   409.5 1058.25   448.5 1050.99   450.8 1051.85   465.8 1057.45
   496.9 1075.85     555 1097.42   603.3 1111.76   622.6 1119.98   632.3 1121.84
   651.6 1130.52   661.3 1132.97   709.6 1152.52     845    1160   912.7 1167.75
#Mann= 3 , 0 , 0
       0      .1       0   450.8    .045       0   465.8      .1       0
Bank Sta=450.8,465.8
XS Rating Curve= 0 ,0
Exp/Cntr=0.3,0.1

Type RM Length L Ch R = 1 ,4583.5  ,452.319,468.826,481.382
XS GIS Cut Line= 3
     1756739.601      383876.863     1756446.366      384027.486
     1755936.812      384251.818
#Sta/Elev= 30
       0 1088.13     9.7 1083.88    19.4 1081.64    87.3  1074.3     126 1072.06
   145.4 1068.16   184.2 1063.69     223 1060.82   300.6 1057.81   403.8 1049.29
   407.8 1049.11   418.8 1051.28   427.3 1053.16   437.1 1058.24   446.9 1065.88
   456.6 1071.45   466.4 1074.95   485.9 1088.34   495.7 1091.23   515.2 1102.13
     525 1104.95   564.1 1124.54   583.6 1138.27   593.4 1140.71   612.9 1148.96
   642.2  1154.3   661.8 1155.86     779 1147.22   837.6 1145.53   886.4 1141.04
#Mann= 3 , 0 , 0
       0      .1       0   403.8    .045       0   418.8      .1       0
Bank Sta=403.8,418.8
XS Rating Curve= 0 ,0
Exp/Cntr=0.3,0.1

Type RM Length L Ch R = 1 ,4114.6  ,304.183,302.299,300.93
XS GIS Cut Line= 3
     1756772.335      383706.959     1756414.853      383628.871
     1755879.122        383616.9
#Sta/Elev= 30
       0 1129.48    57.8 1112.85      77  1104.7    96.3 1101.77   125.2 1103.01
   144.4 1099.44     183 1082.56   202.2 1072.18   221.5 1066.74   269.6 1069.88
   279.2 1069.38   298.5 1063.64   308.1 1062.56   327.4 1055.14   356.3 1051.48
   445.9 1045.27   453.6 1045.13   460.9 1045.49   492.6 1047.77   502.3 1050.39
     551 1069.71   570.5 1079.69   599.7 1090.83     629 1099.16   648.5 1101.67
   677.7 1109.01   784.9 1144.88   804.3 1149.21   843.3 1154.78   901.8 1159.62
#Mann= 3 , 0 , 0
       0      .1       0   445.9    .045       0   460.9      .1       0
Bank Sta=445.9,460.9
XS Rating Curve= 0 ,0
Exp/Cntr=0.3,0.1

Type RM Length L Ch R = 1 ,3812.3  ,384.288,400,412.498
XS GIS Cut Line= 3
     1756783.008      383333.785      1756316.68       383348.76
     1755863.722       383348.76
#Sta/Elev= 30
       0 1170.58    38.9 1160.46    97.2 1141.72   165.2 1114.83   184.7 1104.32
   194.4  1102.5   213.8  1092.8   223.6  1090.8     243 1081.09   252.7 1079.42
   272.2 1071.22   281.9 1069.74   301.3 1061.58   320.8 1057.46   340.2  1056.1
   369.4 1047.55   437.4 1044.84   459.1 1041.91   466.6 1041.88   474.1 1043.32
   495.5 1048.61   543.7 1068.57   620.8 1094.09   649.7 1106.68     669 1121.31
   678.6 1124.84   688.2    1131   726.8 1146.65   755.7 1151.48   919.5 1146.48
#Mann= 3 , 0 , 0
       0      .1       0   459.1    .045       0   474.1      .1       0
Bank Sta=459.1,474.1
XS Rating Curve= 0 ,0
Exp/Cntr=0.3,0.1

Type RM Length L Ch R = 1 ,3412.3  ,399.715,400,402.739
XS GIS Cut Line= 3
     1756778.058      382955.499     1756321.604      382988.886
     1755872.107      383070.228
#Sta/Elev= 30
       0 1131.52    48.7 1130.39    87.6 1134.03   107.1  1133.8   126.6 1128.87
   155.8  1118.6   165.5 1114.48   175.3 1108.51   204.5 1095.85   243.4 1082.58
   301.9 1070.44   340.8 1063.73   350.6  1060.8     370 1049.49   389.5  1044.2
   418.7 1047.01   438.2 1043.31   450.2 1037.89   457.7 1036.41   465.2 1036.71
   554.9 1049.37   632.6 1063.67   778.4 1087.72   807.6 1094.39     827 1102.04
   836.7 1103.74   856.2 1111.56   885.3 1120.01     895 1120.56   914.5 1125.73
#Mann= 3 , 0 , 0
       0      .1       0   450.2    .045       0   465.2      .1       0
Bank Sta=450.2,465.2
XS Rating Curve= 0 ,0
Exp/Cntr=0.3,0.1

Type RM Length L Ch R = 1 ,3012.3  ,288.824,286.466,284.109
XS GIS Cut Line= 3
      1756696.88      382573.828      1756242.63      382599.935
     1755788.379      382626.041
#Sta/Elev= 30
       0 1145.84      29 1142.24    48.4 1137.26    67.8 1128.54   116.2 1114.17
   164.6 1094.96   193.6 1085.66   300.1 1064.71   329.1 1056.91   348.5 1048.75
   367.9  1042.9   416.3 1041.98     426  1039.8   435.6 1035.41   447.5 1033.24
     455 1033.16   462.5 1035.45   474.4 1039.31   493.7 1056.22   522.8 1070.88
   532.4 1073.31   561.5 1086.64   600.2 1099.68   619.6 1109.72   629.3 1111.69
   677.7 1132.76   687.3 1134.86   706.7 1143.54   735.7  1151.8     910 1170.02
#Mann= 3 , 0 , 0
       0      .1       0   447.5    .045       0   462.5      .1       0
Bank Sta=447.5,462.5
XS Rating Curve= 0 ,0
Exp/Cntr=0.3,0.1

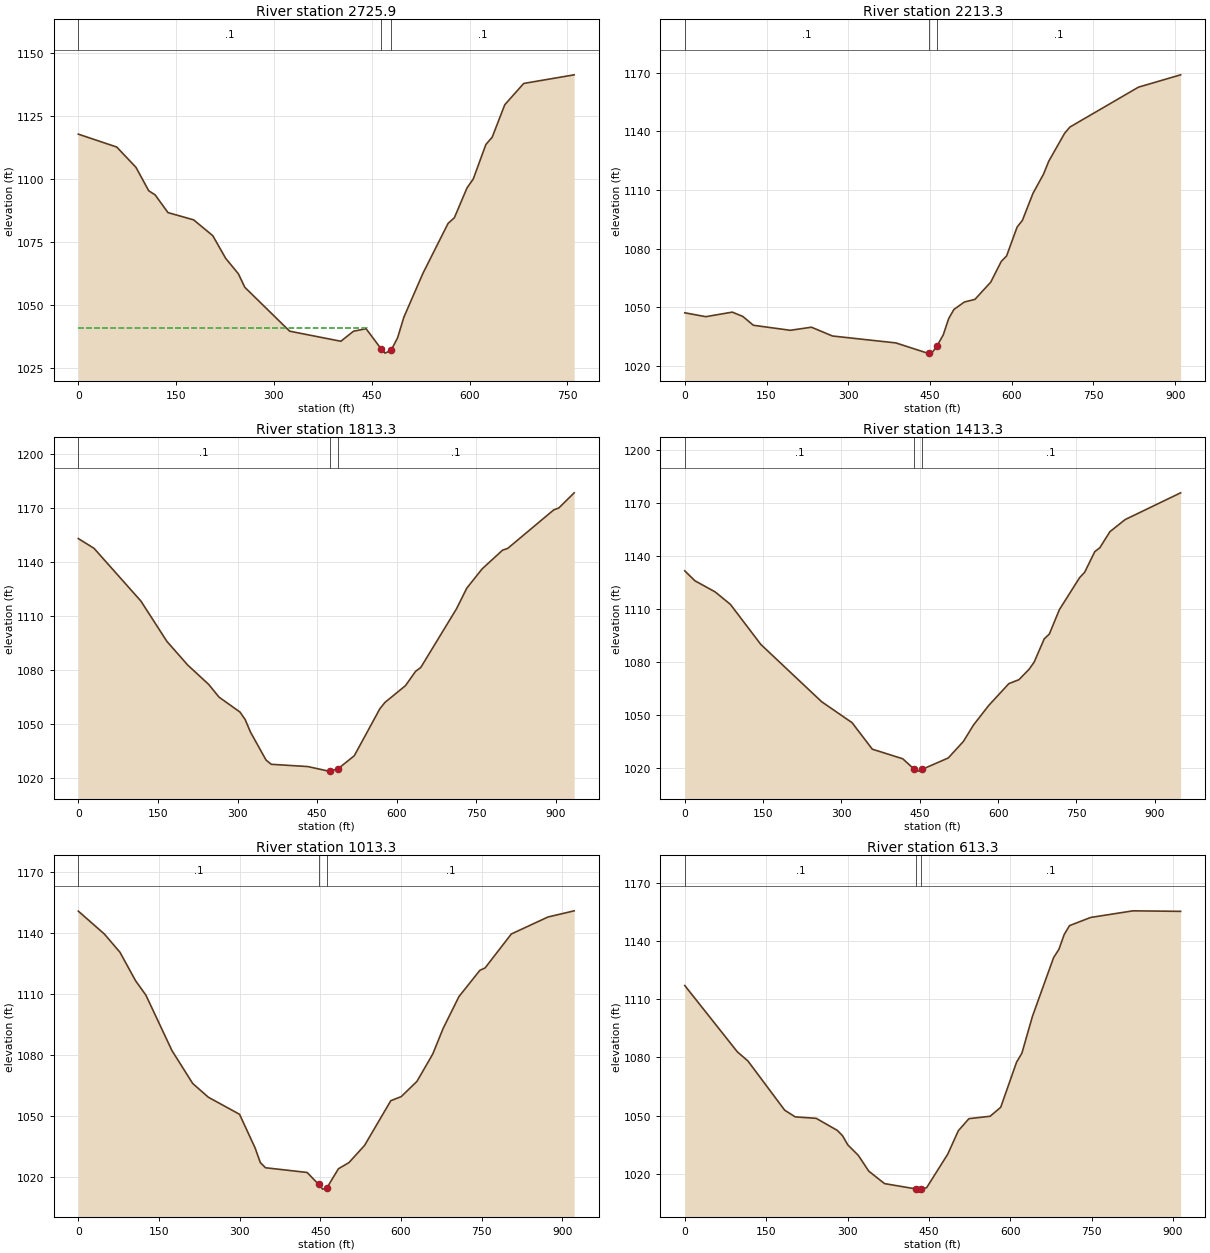
Type RM Length L Ch R = 1 ,2725.9  ,505.776,512.553,519.653
XS GIS Cut Line= 3
     1756695.947      382365.028      1756298.13      382303.013
     1755944.824      382359.416
#Sta/Elev= 30
       0 1117.86    58.9 1112.75    88.4  1104.7     108 1095.39   117.8 1093.78
   137.5 1086.75   176.8 1083.88   206.2  1077.6   225.9 1068.64   245.5 1062.47
   255.3 1057.14   324.1 1039.73   402.6 1035.74     422 1039.71   441.3 1040.72
   464.6 1032.64   470.3 1031.03   479.6 1032.11   489.6 1037.11   499.3 1045.31
   528.3 1062.57     567 1082.45   576.7 1084.72     596  1096.5   605.7  1100.1
     625 1113.75   634.7 1116.65     654 1129.52     683 1137.96   760.4 1141.38
#Mann= 3 , 0 , 0
       0      .1       0   464.6    .045       0   479.6      .1       0
#XS Ineff= 2 , 0
          442.87 1040.96
Permanent Ineff=
       F       F
Bank Sta=464.6,479.6
XS Rating Curve= 0 ,0
Exp/Cntr=0.3,0.1

Type RM Length L Ch R = 1 ,2213.3  ,406.228,400,388.251
XS GIS Cut Line= 3
     1756769.117      381901.864      1756320.41      381826.109
     1755872.906      381743.915
#Sta/Elev= 30
       0 1047.12    38.7 1045.14    87.1 1047.47   106.5 1045.26   125.9 1040.74
   193.6 1038.17   232.4 1039.75   271.1 1035.25   387.3 1031.72   445.4 1026.49
   447.6 1026.65   455.1  1027.2   462.6 1030.02   474.4 1035.86   484.1 1044.01
   493.8  1048.8   513.1 1052.64   532.5 1053.99   561.5 1062.81   580.9 1073.44
   590.6 1076.21   609.9 1090.98   619.6 1094.41     639 1108.21   658.4 1118.09
     668 1124.68   697.1 1138.97   706.8 1142.15   832.6 1162.56     910 1168.87
#Mann= 3 , 0 , 0
       0      .1       0   447.6    .045       0   462.6      .1       0
Bank Sta=447.6,462.6
XS Rating Curve= 0 ,0
Exp/Cntr=0.3,0.1

Type RM Length L Ch R = 1 ,1813.3  ,401.435,400,399.237
XS GIS Cut Line= 3
     1756788.418       381385.27     1756310.185      381441.664
     1755881.252       381587.14
#Sta/Elev= 30
       0  1153.1    29.5 1147.71   117.9 1118.36   167.1 1095.86   206.4 1082.69
   245.7    1072   265.3 1064.89   304.7 1056.61   314.5 1052.43   324.3 1045.57
   353.8 1029.91   363.6 1027.56   432.4  1026.3   471.7 1023.76     474 1023.84
     489 1024.95   520.1 1032.32   568.3 1058.45   577.9 1061.98   616.5 1071.28
   635.7 1079.29   645.4  1081.4   712.8 1114.07   732.1 1125.51     761 1136.23
   799.6 1146.67   809.2 1147.62   895.9 1169.04   905.6 1170.12   934.5 1178.55
#Mann= 3 , 0 , 0
       0      .1       0     474    .045       0     489      .1       0
Bank Sta=474,489
XS Rating Curve= 0 ,0
Exp/Cntr=0.3,0.1

Type RM Length L Ch R = 1 ,1413.3  ,393.423,400,403.652
XS GIS Cut Line= 3
     1756713.651      380953.819      1756290.06      381095.015
     1755827.819      381293.729
#Sta/Elev= 30
       0 1131.65    19.4 1126.03    58.2 1119.71    87.4 1112.64   145.6 1089.95
   262.1 1057.46   320.3 1045.61   359.1 1030.57   417.4 1025.12     439 1019.31
   446.5 1018.12     454 1019.06   504.6 1025.59   533.6 1034.97   552.9 1044.25
     582 1055.32   620.7 1067.73     640 1069.97   659.4 1075.87     669 1079.86
   688.4 1093.12   698.1 1095.81   717.4 1109.66   756.1  1127.8   765.8 1130.84
   785.2 1142.54   794.8 1144.73   814.2 1153.87   843.2  1160.7   949.6 1175.89
#Mann= 3 , 0 , 0
       0      .1       0     439    .045       0     454      .1       0
Bank Sta=439,454
XS Rating Curve= 0 ,0
Exp/Cntr=0.3,0.1

Type RM Length L Ch R = 1 ,1013.3  ,403.738,400,395.63
XS GIS Cut Line= 3
     1756547.091      380567.806     1756154.254      380796.376
     1755716.279      380960.116
#Sta/Elev= 30
       0 1150.57    48.4 1139.34    77.4 1130.39   106.4 1116.42   125.7 1109.29
   174.1 1082.09   212.7 1065.91   241.8 1059.16   299.8 1050.78   328.8 1034.22
   338.5 1027.04   348.1 1024.51   425.5  1022.2     447 1016.31   454.5 1014.01
     462 1014.52   483.7 1024.02   503.2 1027.02   532.4 1035.52   581.1 1057.45
   600.6 1059.48   629.8 1066.97   659.1 1080.37   678.5 1092.99   707.8 1108.58
   746.7 1121.49   756.5 1122.69   805.2 1139.34   873.4  1147.7   922.1 1150.73
#Mann= 3 , 0 , 0
       0      .1       0     447    .045       0     462      .1       0
Bank Sta=447,462
XS Rating Curve= 0 ,0
Exp/Cntr=0.3,0.1

Type RM Length L Ch R = 1 ,613.3   ,397.873,400,398.852
XS GIS Cut Line= 3
     1756322.311      380160.072      1755980.53      380461.123
     1755591.308      380703.399
#Sta/Elev= 30
       0 1117.02    96.9 1082.88   116.3 1078.21   184.1 1052.85   203.5 1049.41
   242.3 1048.65     281 1042.46   290.7 1039.73   300.4 1035.02   319.8  1029.6
   339.2 1021.44   368.2 1015.05   426.4  1012.3   436.1 1012.21   445.8 1012.97
   484.7 1030.24   504.2 1042.28   523.7 1048.48   562.8 1049.73   582.3 1054.35
   611.5 1077.56   621.3 1082.18   640.8 1101.19   679.8 1131.44   689.6 1135.68
   699.3 1143.29   709.1 1147.87   748.1 1152.08   826.1 1155.49   913.9 1155.22
#Mann= 3 , 0 , 0
       0      .1       0   426.4    .045       0   436.1      .1       0
Bank Sta=426.4,436.1
XS Rating Curve= 0 ,0
Exp/Cntr=0.3,0.1

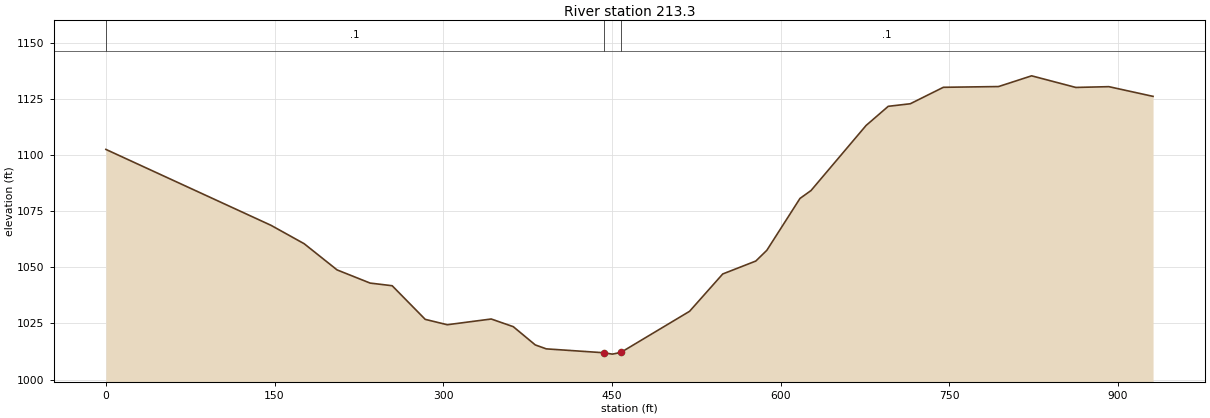
Type RM Length L Ch R = 1 ,213.3   ,208.89,213.324,217.297
XS GIS Cut Line= 3
     1756134.917      379871.914     1755769.754      380135.643
     1755374.261      380409.112
#Sta/Elev= 30
       0 1102.47   146.9 1068.65   176.3 1060.48   205.6 1048.81     235 1042.94
   254.6 1041.76     284 1026.78   303.6 1024.39   342.7 1026.94   362.3 1023.53
   381.9 1015.39   391.7 1013.64   442.9 1011.91   450.4  1011.3   457.9 1012.03
   519.1 1030.37   548.6    1047     578 1052.75   587.8 1057.53   617.3 1080.64
   627.1 1084.15   676.1 1113.14   695.8 1121.66   715.4  1122.8   744.8 1130.13
   793.9 1130.46   823.3 1135.24   862.6 1130.07     892 1130.41   931.3 1126.09
#Mann= 3 , 0 , 0
       0      .1       0   442.9    .045       0   457.9      .1       0
Bank Sta=442.9,457.9
XS Rating Curve= 0 ,0
Exp/Cntr=0.3,0.1

Chan Stop Cuts=-1
Use User Specified Reach Order=0